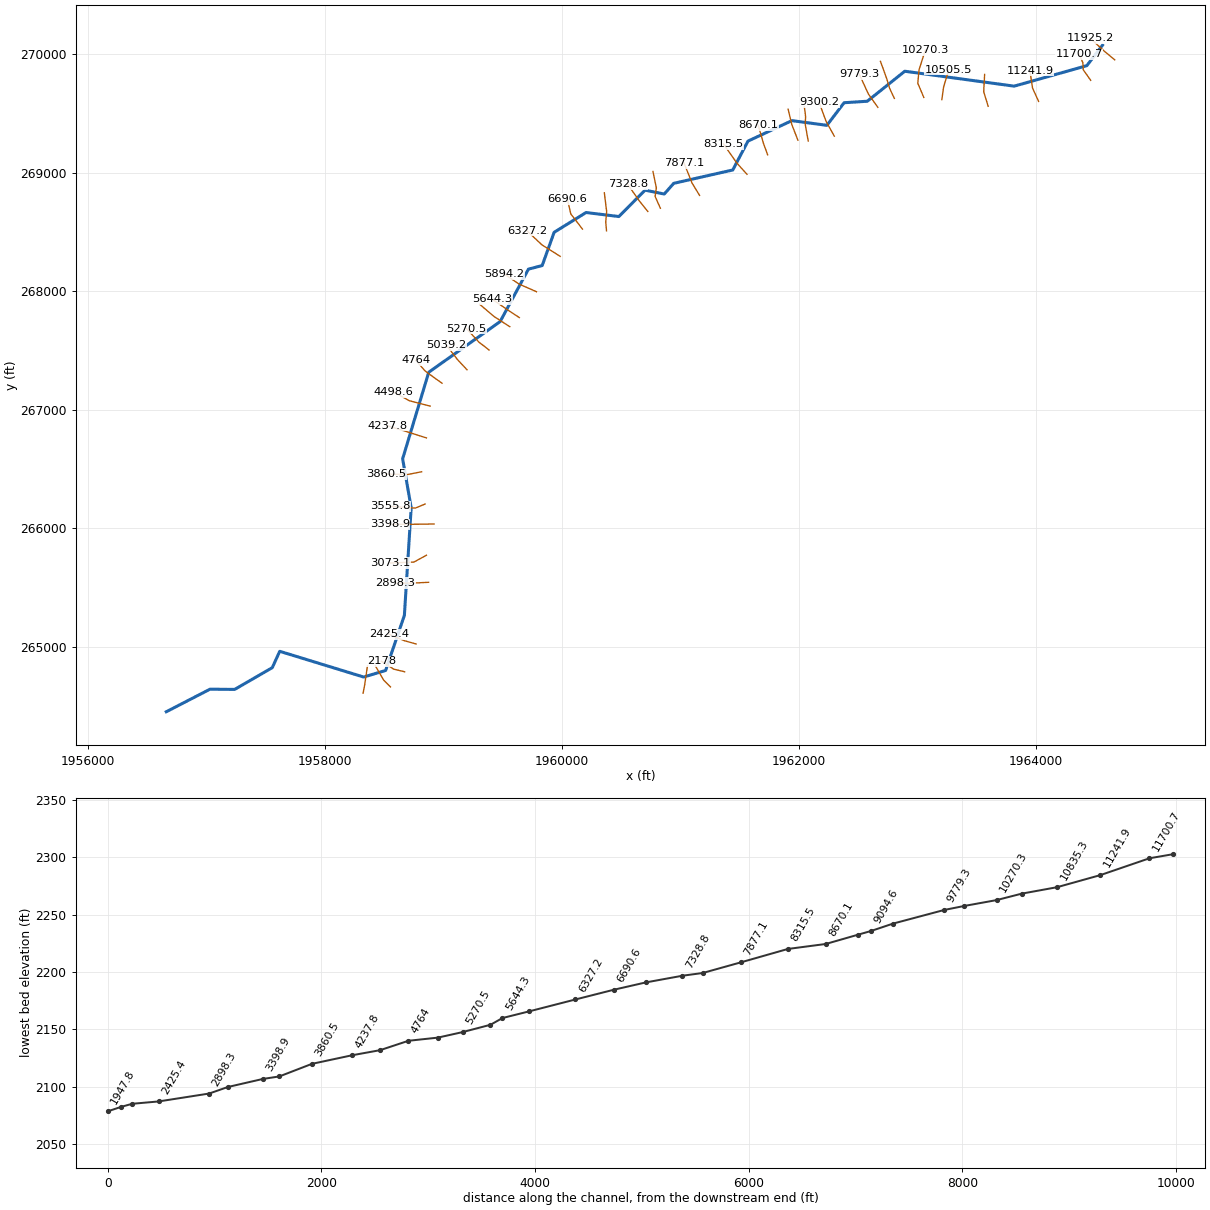
--- WOLFRN1.prj (project) ---

Proj Title=WOLFRN1
Current Plan=p01
Default Exp/Contr=0,0
English Units
Geom File=g01
Flow File=f01
Plan File=p01
BEGIN DESCRIPTION:
END DESCRIPTION:
DSS Export Rating Curves= 0
DSS Export Rating Curve Sorted= 0
DSS Export Volume Flow Curves= 0
DXF OffsetX= 0
DXF OffsetY= 0
DXF ScaleX= 0
DXF ScaleY= 0

--- WOLFRN1.p01 (plan) ---

Plan Title=Floodplain
Program Version=4.00
Geom File=g01
Flow File=f01
K Sum by GR=0
Std Step Tol=0.01
Critical Tol=0.01
Num of Std Step Trials=20
Max Error Tol=0.3
Flow Tol Ratio=0.001
Split Flow NTrial=30
Split Flow Tol=0.02
Split Flow Ratio=0.02
Log Output Level=0
Friction Slope Method=1
Unsteady Friction Slope Method=2
Unsteady Bridges Friction Slope Method=1
Global Log Level=0
CheckData=False
Run HTab=0
Run UNet=0
Run PostProcess=0
UNET Theta=0
UNET Theta Warmup=0
UNET ZTol=0
UNET ZSATol=0
UNET MxIter=0
UNET MaxInSteps=0
UNET DtIC=0
UNET DtMin=0
UNET MaxCRTS=0
UNET WFStab=0
UNET SFStab=0
UNET WFX=0
UNET SFX=0
UNET DSS MLevel=0
UNET DZMax Abort=0
UNET Convert EG Bridges=0
UNET Use Existing IB Tables=0
UNET Froude Limit=0
UNET Froude Power=0
Write IC File=0
Echo Input=False
Echo Output=False
Write Detailed=0

--- WOLFRN1.f01 (steady flow) ---

Flow Title=NFF Regression Equation
Program Version=4.00
Number of Profiles=1
Profile Names=P100yr
River Rch & RM=WOLFRN1,Main      ,11925.2
517.8204
River Rch & RM=WOLFRN1,Main      ,10270.3
565.4337
River Rch & RM=WOLFRN1,Main      ,9966.3
622.6531
River Rch & RM=WOLFRN1,Main      ,6690.6
673.7732
River Rch & RM=WOLFRN1,Main      ,4237.8
734.8112
River Rch & RM=WOLFRN1,Main      ,3398.9
802.7098
River Rch & RM=WOLFRN1,Main      ,408.3
862.7308
Boundary for River Rch & Prof#=WOLFRN1,Main      ,1
Up Type=0
Dn Type=3
Dn Slope=0.019391

--- WOLFRN1.g01 (geometry) ---

Geom Title=USGS 10m DEM
Program Version=4.10

River Reach=WOLFRN1         ,Main
Reach XY= 30
       1964558.6      270075.124     1964426.297      269902.421
      1963813.45      269729.678     1962890.622      269855.517
     1962574.301      269602.507     1962378.585      269589.899
     1962233.515       269399.34     1961938.067      269438.872
     1961567.356      269266.136     1961439.344      269022.749
     1960941.271      268910.233     1960860.934       268819.89
     1960699.301      268852.724     1960478.393      268630.201
     1960201.587      268664.052     1959932.157      268497.364
     1959831.245      268216.874     1959715.125      268186.481
     1959476.427      267744.326     1958874.148      267317.105
     1958653.965      266587.187      1958725.91      266175.267
     1958668.598      265267.046     1958510.282      264802.377
     1958325.386      264746.822     1957616.729      264963.899
     1957554.285      264826.215     1957236.844      264642.655
     1957028.511      264644.391     1956660.021      264454.287

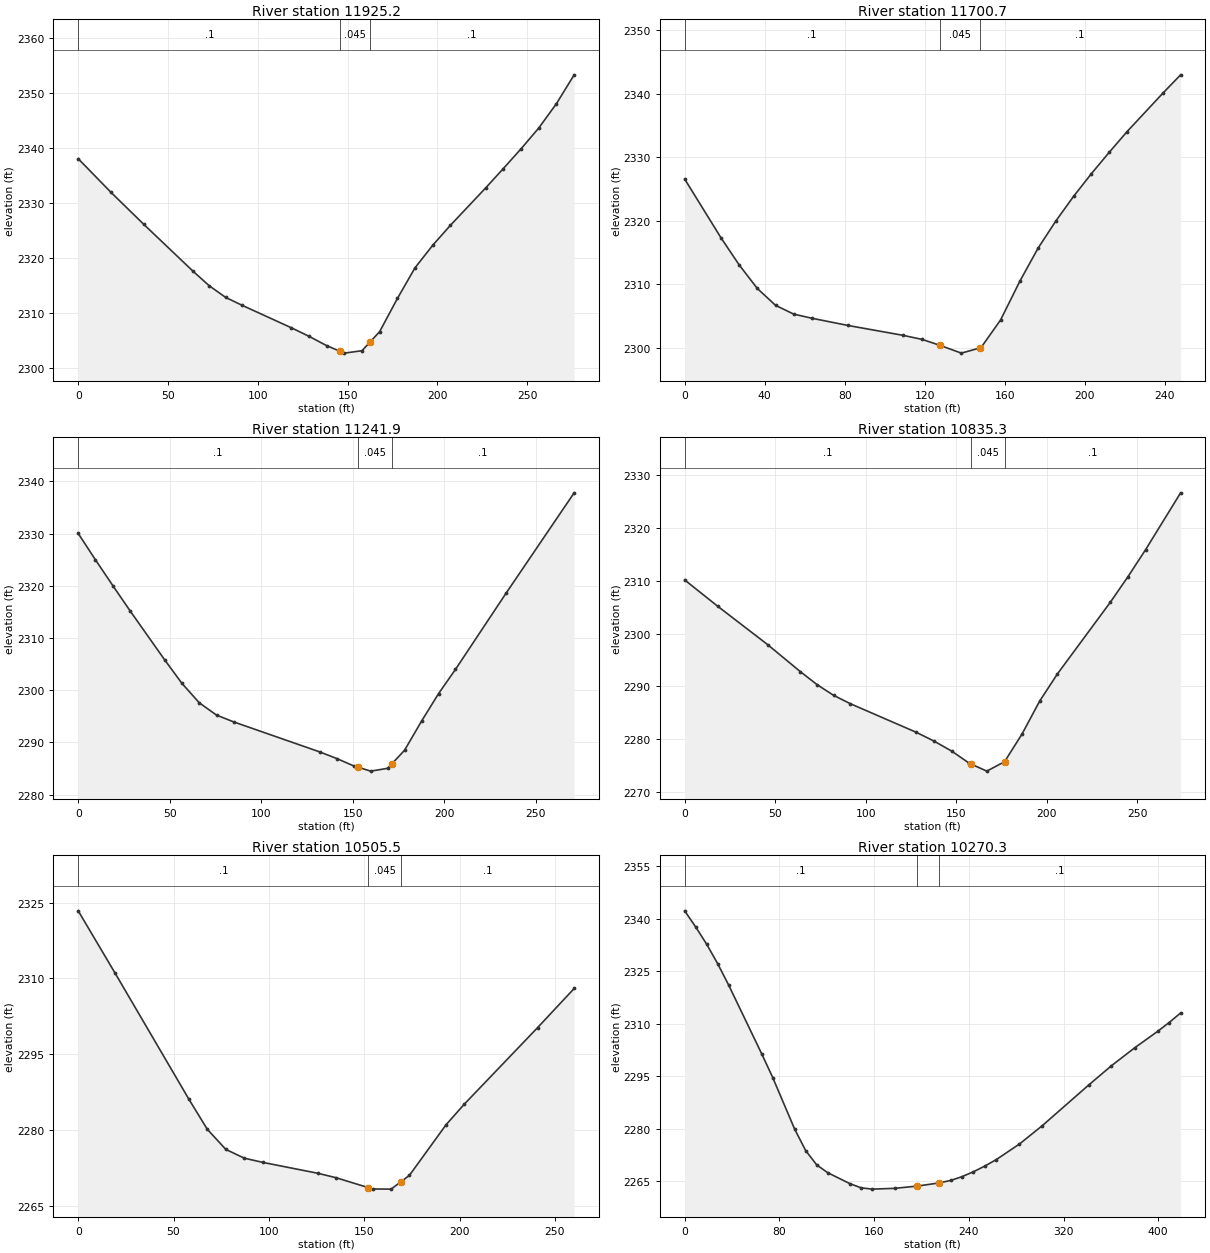
Type RM Length L Ch R = 1 ,11925.2 ,242.1,224.6,206.9
XS GIS Cut Line= 3
     1964662.202      269951.285     1964571.056       270027.24
     1964454.954      270133.577
#Sta/Elev= 25
       0 2338.06    18.2 2331.97    36.5 2326.15    63.9 2317.65      73 2314.99
    82.1 2312.89    91.3 2311.45   118.6 2307.39   128.5 2305.83   138.3 2304.14
     1462303.082   148.2 2302.78     158 2303.22  162.422304.779   167.8 2306.67
   177.7  2312.7   187.5 2318.26   197.4 2322.37   207.2 2325.97   226.9 2332.78
   236.7 2336.28   246.6 2339.88   256.4 2343.63   266.2 2348.03   276.1 2353.28
#Mann= 3 , 0 , 0
       0      .1       0     146    .045       0  162.42      .1       0
Bank Sta=146,162.42
XS Rating Curve= 0 ,0
Exp/Cntr=0.3,0.1

Type RM Length L Ch R = 1 ,11700.7 ,456.4,458.7,460.9
XS GIS Cut Line= 4
     1964459.294      269778.759      1964396.36      269867.735
     1964393.105      269926.328     1964361.638      270000.113
#Sta/Elev= 24
       0 2326.57    18.2  2317.3    27.2 2313.08    36.3 2309.35    45.4  2306.7
    54.5 2305.31    63.6 2304.66    81.7 2303.52     109 2301.98   118.8 2301.32
   127.52300.405   138.3 2299.17   147.52299.978   148.1 2300.03   157.9 2304.39
   167.7 2310.59   176.6 2315.67   185.5 2319.96   194.4 2323.85   203.3 2327.42
   212.2 2330.78   221.1 2334.03     239 2340.08   247.9 2342.98
#Mann= 3 , 0 , 0
       0      .1       0   127.5    .045       0   147.5      .1       0
Bank Sta=127.5,147.5
XS Rating Curve= 0 ,0
Exp/Cntr=0.3,0.1

Type RM Length L Ch R = 1 ,11241.9 ,411.1,406.6,401.7
XS GIS Cut Line= 3
     1964019.841      269600.807     1963968.843       269712.57
     1963946.056      269859.054
#Sta/Elev= 22
       0 2330.02     9.4 2324.98    18.9 2320.04    28.4 2315.18    47.2 2305.85
    56.7 2301.32    66.2 2297.59    75.6 2295.25      85 2293.94   132.1 2288.19
   141.4 2286.92   150.6 2285.52   152.72285.296   159.9 2284.52   169.2 2285.06
  171.332285.865   178.4 2288.52   187.7  2294.1     197 2299.37   206.2 2303.98
     234 2318.64   271.1 2337.79
#Mann= 3 , 0 , 0
       0      .1       0   152.7    .045       0  171.33      .1       0
Bank Sta=152.7,171.33
XS Rating Curve= 0 ,0
Exp/Cntr=0.3,0.1

Type RM Length L Ch R = 1 ,10835.3 ,335.1,329.9,324.4
XS GIS Cut Line= 3
      1963594.06      269560.226     1963556.299      269682.622
     1963564.112      269828.455
#Sta/Elev= 21
       0 2310.16    18.3 2305.16    45.8 2297.92      64 2292.77    73.2 2290.32
    82.3  2288.3    91.5 2286.72   128.1 2281.28   137.8 2279.63   147.6 2277.73
   157.3 2275.43   158.42275.262     167 2273.94   176.8 2275.73   186.5    2281
   196.2 2287.21     206 2292.35   235.2 2305.91   244.9 2310.72   254.7 2315.87
   274.1 2326.66
#Mann= 3 , 0 , 0
       0      .1       0   158.4    .045       0   176.8      .1       0
Bank Sta=158.4,176.8
XS Rating Curve= 0 ,0
Exp/Cntr=0.3,0.1

Type RM Length L Ch R = 1 ,10505.5 ,230.6,235.2,239.8
XS GIS Cut Line= 3
     1963203.435      269616.215     1963217.758      269721.684
     1963262.029       269868.82
#Sta/Elev= 18
       0 2323.38    19.4 2311.02    58.1 2286.09    67.7 2280.18    77.4  2276.2
    87.1 2274.46    96.8 2273.63   125.6 2271.48   135.2  2270.6   152.22268.634
   154.4 2268.37   164.1 2268.34  169.342269.828   173.7 2271.06   192.9 2281.06
   202.5 2285.15   240.9 2300.27   260.1 2308.02
#Mann= 3 , 0 , 0
       0      .1       0   152.2    .045       0  169.34      .1       0
Bank Sta=152.2,169.34
XS Rating Curve= 0 ,0
Exp/Cntr=0.3,0.1

Type RM Length L Ch R = 1 ,10270.3 ,295.1,304,312.3
XS GIS Cut Line= 4
     1963051.091      269634.445      1963000.31      269754.236
     1963010.726      269867.518     1963064.112      270034.184
#Sta/Elev= 30
       0 2342.31     9.3  2337.7    18.6 2332.75    27.9 2327.18    37.2 2321.04
    65.1 2301.39    74.4 2294.61    92.9 2279.87   102.2 2273.75   111.5 2269.66
   120.8 2267.42   139.6 2264.28   149.1 2263.08   158.6 2262.72   177.5 2262.95
   196.5 2263.59   215.2 2264.51   224.9 2265.22   234.4 2266.31   243.9 2267.69
   253.6 2269.33   263.3 2271.19   282.8 2275.63   302.2 2280.91   341.1 2292.45
   360.5 2298.02     380 2303.11   399.4 2307.82   409.2 2310.37   418.9  2313.1
#Mann= 3 , 0 , 0
       0      .1       0   196.5    .045       0   215.2      .1       0
Bank Sta=196.5,215.2
XS Rating Curve= 0 ,0
Exp/Cntr=0.3,0.1

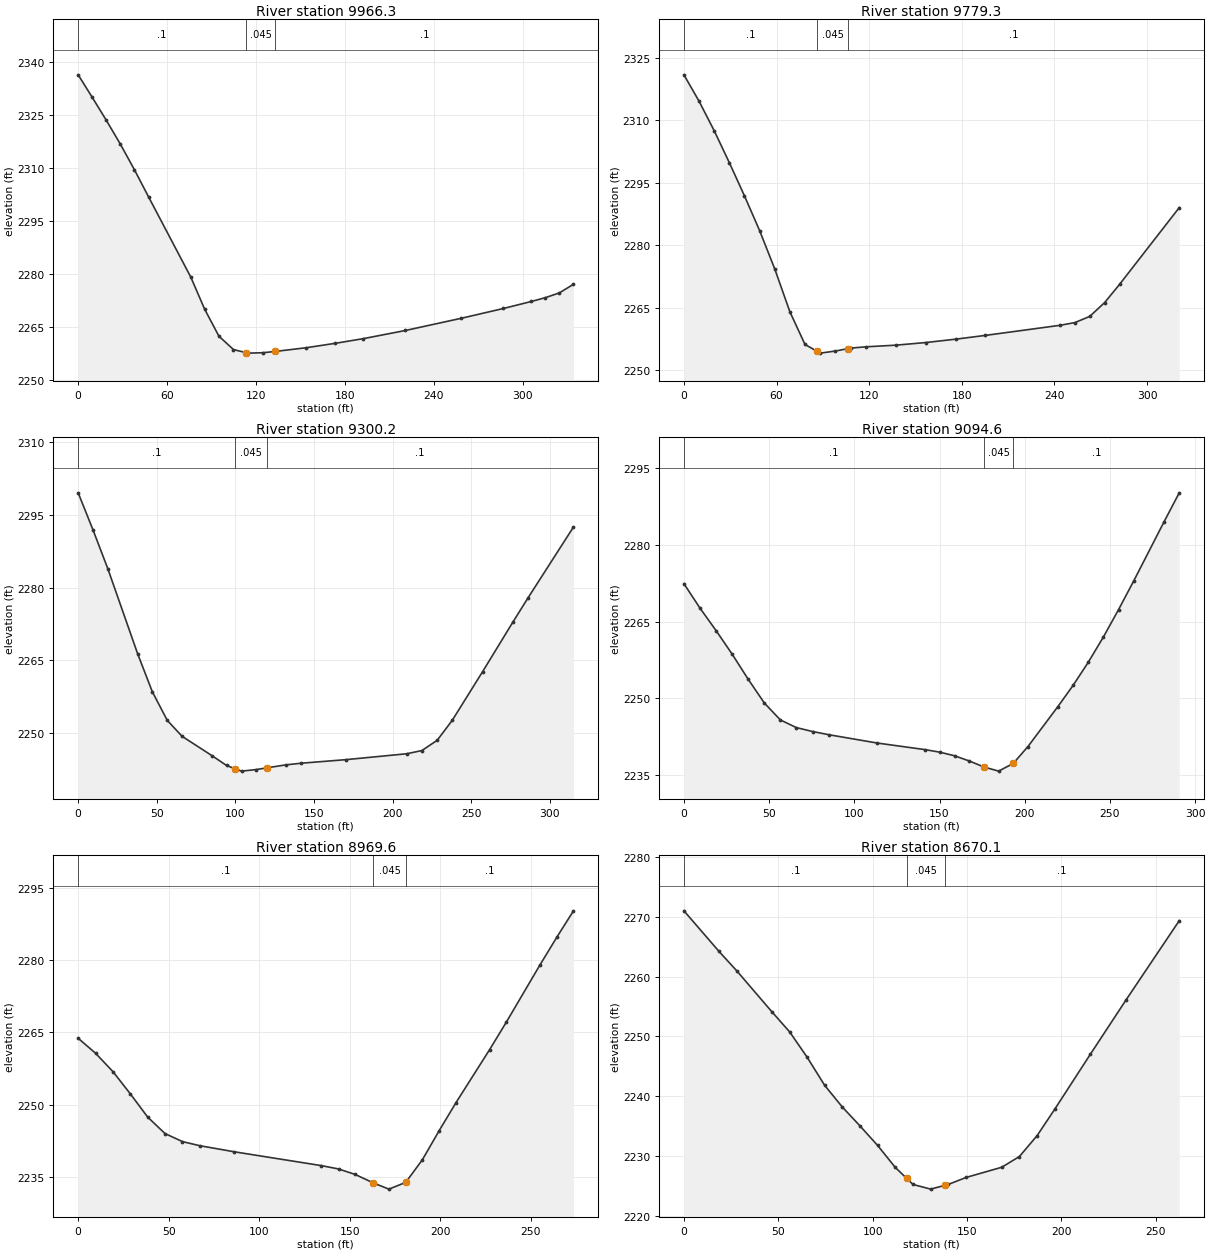
Type RM Length L Ch R = 1 ,9966.3  ,179.5,187,194.6
XS GIS Cut Line= 4
     1962802.393      269626.632     1962762.029       269712.57
     1962739.893       269788.09     1962685.206      269939.132
#Sta/Elev= 24
       0 2336.32     9.5 2329.94      19 2323.45    28.5 2316.69      38 2309.44
    47.5 2301.79      76 2279.09    85.4 2269.98      95 2262.37   104.8 2258.59
   113.12257.735   114.6 2257.58   124.5 2257.69   133.12258.058     154 2259.11
   173.6 2260.36   192.5 2261.68   220.9 2263.99   258.7 2267.45     287 2270.21
   305.9  2272.2   315.4 2273.28   324.8 2274.63   334.3 2277.06
#Mann= 3 , 0 , 0
       0      .1       0   113.1    .045       0   133.1      .1       0
Bank Sta=113.1,133.1
XS Rating Curve= 0 ,0
Exp/Cntr=0.3,0.1

Type RM Length L Ch R = 1 ,9779.3  ,480.8,479.1,476.2
XS GIS Cut Line= 3
      1962663.07      269551.111     1962583.643       269663.09
      1962506.82      269829.757
#Sta/Elev= 25
       0 2320.85     9.8 2314.52    19.6 2307.44    29.4 2299.78    39.2 2291.82
      49  2283.5    58.8 2274.31    68.6 2264.03    78.4 2256.18    86.22254.541
    88.3  2254.1    98.1  2254.6   106.22255.179   107.9  2255.3   117.7 2255.61
   137.3 2256.01   156.6 2256.64   175.9 2257.44   195.2 2258.35   243.5 2260.77
   253.2 2261.42   262.8  2262.9   272.5 2266.23   282.2 2270.62   320.8    2289
#Mann= 3 , 0 , 0
       0      .1       0    86.2    .045       0   106.2      .1       0
Bank Sta=86.2,106.2
XS Rating Curve= 0 ,0
Exp/Cntr=0.3,0.1

Type RM Length L Ch R = 1 ,9300.2  ,217.9,205.6,192.8
XS GIS Cut Line= 3
     1962295.883      269308.273     1962226.872      269431.971
     1962166.976      269594.731
#Sta/Elev= 24
       0 2299.51     9.4  2291.9    18.9 2283.85    37.8  2266.4    47.2 2258.53
    56.7 2252.65    66.1 2249.38      85 2245.42    94.4 2243.37    99.92242.696
   103.9 2242.21   113.3 2242.53   119.92242.884   132.2  2243.5   141.6 2243.83
   170.6 2244.58   209.1 2245.79   218.7 2246.45   228.4 2248.56     238 2252.68
   257.3  2262.7   276.5 2272.87   286.2 2277.89   315.1 2292.47
#Mann= 3 , 0 , 0
       0      .1       0    99.9    .045       0   119.9      .1       0
Bank Sta=99.9,119.9
XS Rating Curve= 0 ,0
Exp/Cntr=0.3,0.1

Type RM Length L Ch R = 1 ,9094.6  ,118.9,125,131.1
XS GIS Cut Line= 4
     1962075.831      269266.606     1962051.091      269405.929
     1962053.695      269474.939     1962043.279      269554.367
#Sta/Elev= 27
       0 2272.39     9.4 2267.63    18.9 2263.21    28.3 2258.63    37.7 2253.73
    47.2 2249.08    56.6 2245.78      66 2244.28    75.5 2243.52    84.9  2242.9
   113.2 2241.28   141.5 2239.98   150.1 2239.49   158.8 2238.78   167.4 2237.77
     176  2236.6   184.7 2235.78   193.3 2237.29   201.9 2240.58   219.5  2248.4
   228.4 2252.53   237.3 2257.04   246.2 2261.99   255.1 2267.34     264 2272.94
   281.8 2284.49   290.7 2290.14
#Mann= 3 , 0 , 0
       0      .1       0     176    .045       0   193.3      .1       0
Bank Sta=176,193.3
XS Rating Curve= 0 ,0
Exp/Cntr=0.3,0.1

Type RM Length L Ch R = 1 ,8969.6  ,298.6,299.4,299.9
XS GIS Cut Line= 3
     1961988.591      269274.419     1961936.508      269408.533
      1961906.56      269534.835
#Sta/Elev= 23
       0 2263.74     9.6 2260.64    19.2 2256.83    28.8 2252.23    38.4  2247.4
      48 2243.98    57.6 2242.32    67.1 2241.47    86.3  2240.2   134.3 2237.34
   143.9 2236.64   153.1  2235.5   163.12233.745   171.7 2232.46     181 2233.86
   190.2 2238.55   199.5  2244.6   208.8 2250.41   227.3 2261.35   236.6 2267.09
   255.1  2278.9   264.4 2284.64   273.7 2290.17
#Mann= 3 , 0 , 0
       0      .1       0   163.1    .045       0     181      .1       0
Bank Sta=163.1,181
XS Rating Curve= 0 ,0
Exp/Cntr=0.3,0.1

Type RM Length L Ch R = 1 ,8670.1  ,343.1,354.7,365.1
XS GIS Cut Line= 3
     1961733.383      269150.721     1961698.226      269247.075
     1961653.956      269400.721
#Sta/Elev= 24
       0 2271.04    18.6 2264.24      28 2260.99    46.6 2254.14      56 2250.78
    65.3 2246.52    74.6 2241.81    83.9  2238.2    93.2 2235.06   102.6 2231.77
     112 2228.08   118.12226.222   121.4 2225.22   130.8 2224.44   138.12225.062
   140.2 2225.24   149.6  2226.4   168.4  2228.1   177.8  2229.9   187.2 2233.41
   196.6 2237.86   215.4 2247.03   234.2 2256.07   262.5 2269.39
#Mann= 3 , 0 , 0
       0      .1       0   118.1    .045       0   138.1      .1       0
Bank Sta=118.1,138.1
XS Rating Curve= 0 ,0
Exp/Cntr=0.3,0.1

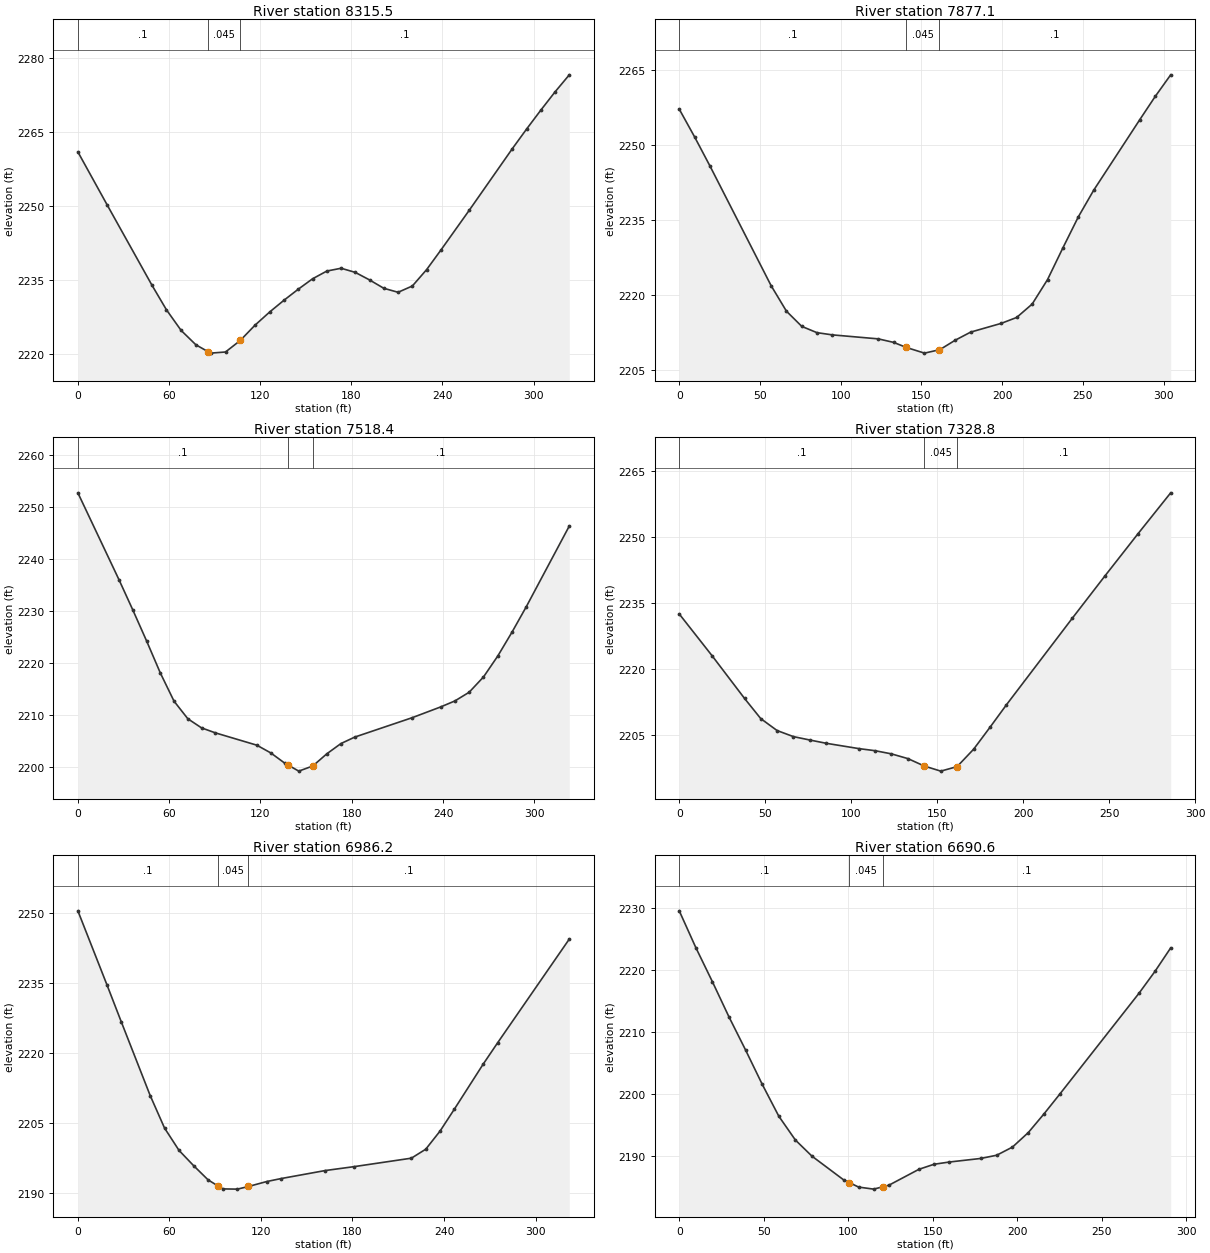
Type RM Length L Ch R = 1 ,8315.5  ,446.3,438.4,430
XS GIS Cut Line= 3
     1961558.904      268986.658     1961474.268      269080.408
     1961360.987      269241.867
#Sta/Elev= 30
       0 2260.95    19.4 2250.12    48.6 2233.98    58.3  2228.9      68  2224.7
    77.7 2221.79   85.922220.358    87.4  2220.1    97.2 2220.33   106.9 2222.67
   116.6 2225.77   126.3 2228.46   135.7 2230.84   145.1 2233.08   154.5 2235.19
   163.9 2236.76   173.3 2237.33   182.6 2236.49     192 2234.96   201.4 2233.26
   210.8 2232.45   220.2 2233.73   229.6 2237.06     239 2241.03   257.8 2249.17
     286  2261.6   295.4 2265.59   304.8 2269.44   314.1 2273.12   323.5 2276.59
#Mann= 3 , 0 , 0
       0      .1       0   85.92    .045       0   106.9      .1       0
Bank Sta=85.92,106.9
XS Rating Curve= 0 ,0
Exp/Cntr=0.3,0.1

Type RM Length L Ch R = 1 ,7877.1  ,371.3,358.7,346.8
XS GIS Cut Line= 3
     1961159.164      268808.273     1961095.362      268913.742
     1961027.654       269081.71
#Sta/Elev= 26
       0  2257.1     9.5 2251.57      19 2245.78    56.9 2221.91    66.4 2216.82
    75.9 2213.79    85.3 2212.54    94.8  2212.1   123.3  2211.3   132.8  2210.6
   140.72209.585   151.9 2208.46   160.7  2209.1   161.4 2209.15   170.9 2211.03
   180.5 2212.65   199.5  2214.4     209 2215.57   218.6 2218.24   228.1 2223.11
   237.6 2229.42   247.2 2235.63   256.7 2240.93   285.3 2255.02   294.8 2259.62
   304.4 2263.94
#Mann= 3 , 0 , 0
       0      .1       0   140.7    .045       0   160.7      .1       0
Bank Sta=140.7,160.7
XS Rating Curve= 0 ,0
Exp/Cntr=0.3,0.1

Type RM Length L Ch R = 1 ,7518.4  ,172.8,189.7,205.6
XS GIS Cut Line= 4
     1960828.435        268700.2     1960784.164      268799.158
     1960794.581      268872.075     1960765.935      269010.096
#Sta/Elev= 27
       0 2252.75    27.1 2235.97    36.1  2230.2    45.2  2224.2    54.2 2218.05
    63.2 2212.62    72.3 2209.22    81.3 2207.47    90.3 2206.52   117.6 2204.14
   126.8 2202.65     136 2200.67   138.32200.287   145.2 2199.14   154.4 2200.13
   163.6 2202.47   172.9 2204.45   182.1 2205.71   219.7 2209.43   238.4  2211.5
   247.8 2212.66   257.2 2214.34   266.6 2217.28     276 2221.32   285.4 2225.94
   294.8 2230.85     323 2246.36
#Mann= 3 , 0 , 0
       0      .1       0   138.3    .045       0   154.4      .1       0
Bank Sta=138.3,154.4
XS Rating Curve= 0 ,0
Exp/Cntr=0.3,0.1

Type RM Length L Ch R = 1 ,7328.8  ,358.1,342.6,326.4
XS GIS Cut Line= 3
     1960722.966      268672.856     1960651.351      268761.398
     1960552.393      268902.023
#Sta/Elev= 22
       0 2232.46      19 2223.02      38 2213.26    47.4 2208.69    56.9 2205.98
    66.4  2204.6    75.9 2203.83    85.4 2203.09   104.4 2201.88   113.9  2201.4
   123.4 2200.68     133  2199.6   142.5 2197.92   152.1 2196.76   161.6 2197.79
   171.2 2201.74   180.8 2206.76   190.3 2211.84   228.5 2231.45   247.6 2241.12
   266.7 2250.64   285.8 2259.98
#Mann= 3 , 0 , 0
       0      .1       0   142.5    .045       0   161.6      .1       0
Bank Sta=142.5,161.6
XS Rating Curve= 0 ,0
Exp/Cntr=0.3,0.1

Type RM Length L Ch R = 1 ,6986.2  ,278.2,295.6,312.6
XS GIS Cut Line= 4
     1960374.008      268510.096     1960367.497      268585.617
      1960375.31      268671.554     1960355.779      268830.408
#Sta/Elev= 23
       0 2250.55      19 2234.75    28.4 2226.82    47.4 2210.98    56.8 2204.02
    66.3 2199.23    75.8 2195.98    85.4  2192.9    91.8 2191.62      95 2190.98
   104.6 2190.93   111.82191.494   123.7 2192.55   133.3  2193.2   162.1 2194.91
   180.9 2195.74   218.6 2197.56     228 2199.48   237.4 2203.37   246.8 2208.08
   265.6 2217.68   275.1 2222.27   322.1  2244.5
#Mann= 3 , 0 , 0
       0      .1       0    91.8    .045       0   111.8      .1       0
Bank Sta=91.8,111.8
XS Rating Curve= 0 ,0
Exp/Cntr=0.3,0.1

Type RM Length L Ch R = 1 ,6690.6  ,355.7,363.3,370.5
XS GIS Cut Line= 4
     1960170.883      268524.419     1960117.497      268594.731
     1960073.226      268650.721     1960043.279      268778.325
#Sta/Elev= 27
       0 2229.53     9.8  2223.6    19.6  2218.1    29.4 2212.43    39.2  2207.1
      49 2201.59    58.9  2196.4    68.7 2192.56    78.5 2189.96    97.2 2186.14
   100.72185.679   106.1 2184.97     115 2184.64   120.72185.037     124 2185.27
   141.8 2187.84   150.7 2188.65   159.7 2189.01   178.4 2189.59   187.8 2190.11
   197.1 2191.42   206.5 2193.77   215.8 2196.79   225.2    2200     272 2216.25
   281.4 2219.76   290.7 2223.55
#Mann= 3 , 0 , 0
       0      .1       0   100.7    .045       0   120.7      .1       0
Bank Sta=100.7,120.7
XS Rating Curve= 0 ,0
Exp/Cntr=0.3,0.1

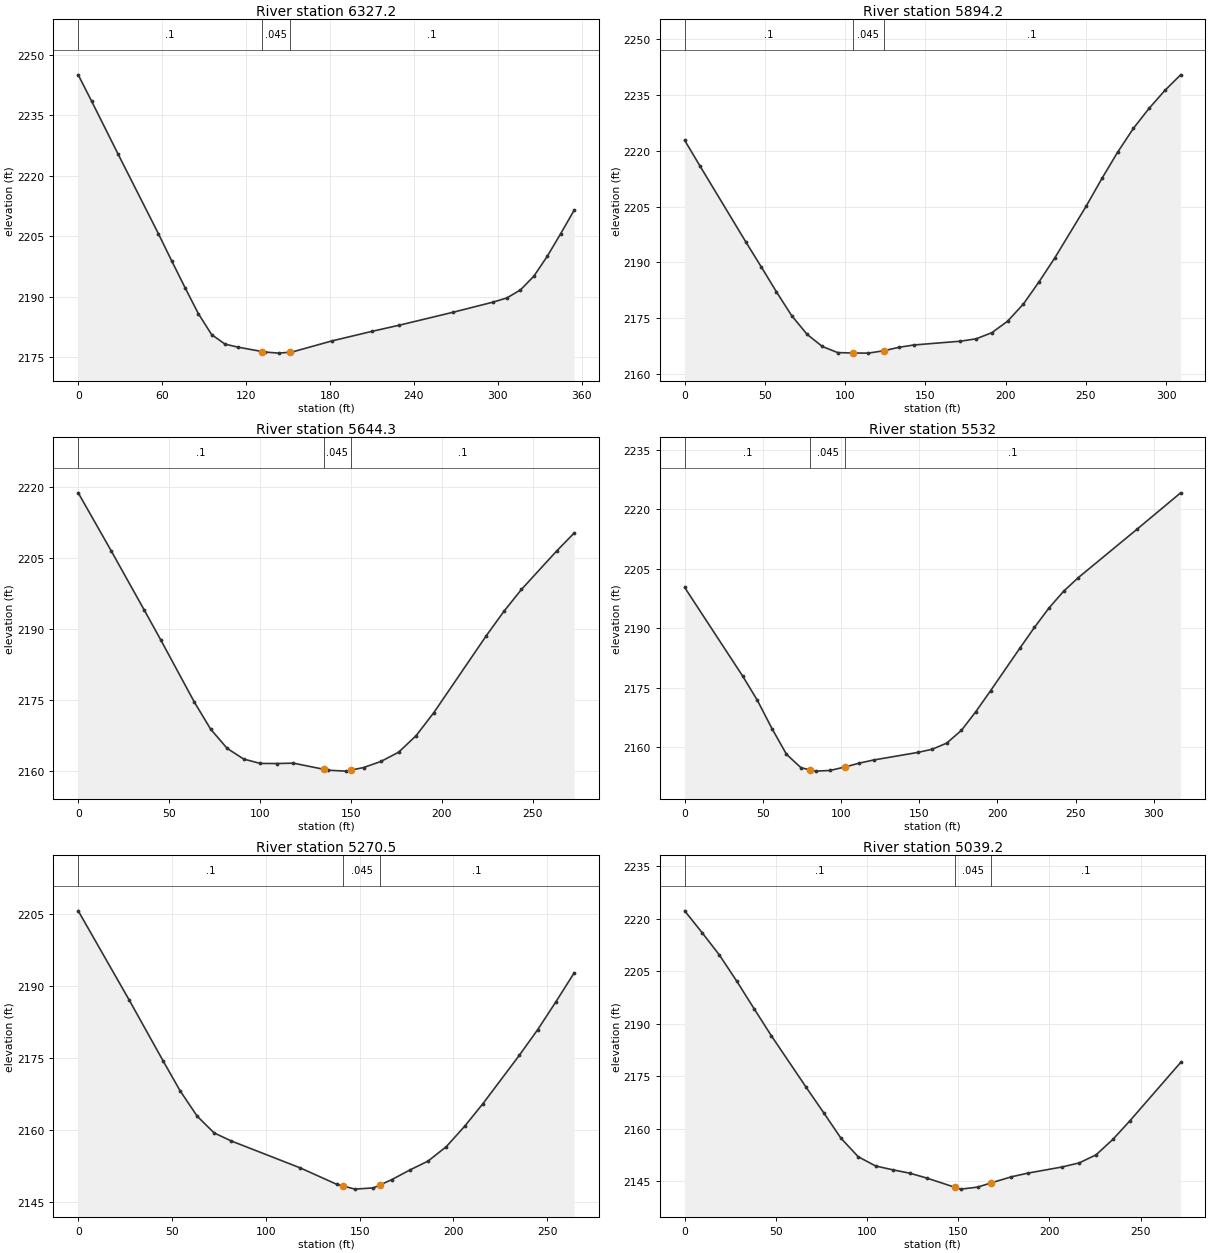
Type RM Length L Ch R = 1 ,6327.2  ,428.2,433.1,439.3
XS GIS Cut Line= 3
     1959983.383      268294.601     1959829.737      268390.955
     1959703.435      268509.445
#Sta/Elev= 26
       0    2245     9.6 2238.46    28.6  2225.3    57.3 2205.66    66.8 2198.94
    76.4 2192.25    85.9 2185.83    95.4 2180.64     105 2178.28   114.5 2177.52
   131.32176.463   133.8 2176.32   143.2 2176.06   151.32176.281   152.7 2176.32
   181.4 2179.09   210.2 2181.47   229.5 2182.98     268 2186.19   296.8 2188.72
   306.4 2189.73   316.1 2191.72   325.7 2195.12   335.3 2200.06   344.9 2205.67
   354.5 2211.47
#Mann= 3 , 0 , 0
       0      .1       0   131.3    .045       0   151.3      .1       0
Bank Sta=131.3,151.3
XS Rating Curve= 0 ,0
Exp/Cntr=0.3,0.1

Type RM Length L Ch R = 1 ,5894.2  ,254.8,249.9,243.3
XS GIS Cut Line= 3
     1959782.862      267996.424     1959634.424      268061.528
     1959513.331      268144.861
#Sta/Elev= 28
       0 2222.75     9.5 2215.89    38.1 2195.52    47.7 2188.84    57.2 2182.13
    66.7 2175.74    76.3 2170.74    85.8 2167.48    95.4 2165.84   104.9 2165.73
   114.4  2165.7     124 2166.33   133.5 2167.26     143 2167.89   171.9  2168.9
   181.7 2169.54   191.5 2171.19   201.3 2174.28   211.1 2178.86   220.9 2184.84
   230.7 2191.24   250.3 2205.14   260.1 2212.56   269.9  2219.6   279.7 2225.97
   289.5 2231.34   299.3 2236.12   309.1  2240.3
#Mann= 3 , 0 , 0
       0      .1       0   104.9    .045       0     124      .1       0
Bank Sta=104.9,124
XS Rating Curve= 0 ,0
Exp/Cntr=0.3,0.1

Type RM Length L Ch R = 1 ,5644.3  ,111.6,112.3,112.9
XS GIS Cut Line= 3
     1959638.349      267778.021     1959539.607      267843.125
     1959412.654      267931.016
#Sta/Elev= 25
       0 2218.87    18.2 2206.53    36.4 2193.96    45.5 2187.62    63.7 2174.62
    72.8 2168.79    81.9  2164.7      91 2162.44   100.1 2161.51   109.2 2161.49
   118.3 2161.57   134.9 2160.28   137.6 2160.07   147.2 2159.88   149.9 2160.09
   156.9 2160.64   166.5 2161.94   176.2  2163.9   185.8  2167.4   195.5 2172.26
   224.4 2188.59   234.1 2193.76   243.7 2198.38     263 2206.51   272.7 2210.35
#Mann= 3 , 0 , 0
       0      .1       0   134.9    .045       0   149.9      .1       0
Bank Sta=134.9,149.9
XS Rating Curve= 0 ,0
Exp/Cntr=0.3,0.1

Type RM Length L Ch R = 1 ,5532    ,267.3,261.5,255.6
XS GIS Cut Line= 3
     1959557.601      267701.502     1959424.789      267787.439
     1959303.695      267890.304
#Sta/Elev= 25
       0 2200.29    37.2 2177.88    46.5 2171.83    55.8 2164.74    65.1 2158.24
    74.4 2154.85   80.292154.317    83.8    2154      93 2154.17   102.4 2155.04
   111.7 2156.02     121 2156.82   148.9  2158.7   158.2 2159.51   167.5 2161.05
   176.9 2164.26   186.2 2169.01   195.6 2174.28   214.3 2184.98   223.6 2190.21
     233 2195.15   242.3 2199.34   251.6 2202.74     289  2214.9   317.1 2224.14
#Mann= 3 , 0 , 0
       0      .1       0   80.29    .045       0   102.4      .1       0
Bank Sta=80.29,102.4
XS Rating Curve= 0 ,0
Exp/Cntr=0.3,0.1

Type RM Length L Ch R = 1 ,5270.5  ,233.2,231.4,229.5
XS GIS Cut Line= 3
     1959383.122      267504.887     1959297.185      267571.294
     1959191.716      267685.877
#Sta/Elev= 23
       0 2205.64    27.2 2187.02    45.2 2174.38    54.3 2168.12    63.4 2162.82
    72.4 2159.34    81.4 2157.68   118.3 2152.04   137.8 2148.61     1412148.279
   147.5 2147.61   157.3 2147.87     1612148.518     167 2149.57   176.7 2151.59
   186.5 2153.47   196.2 2156.48   205.9  2160.7   215.7 2165.44   235.1 2175.53
   244.9 2180.88   254.6 2186.69   264.3  2192.7
#Mann= 3 , 0 , 0
       0      .1       0     141    .045       0     161      .1       0
Bank Sta=141,161
XS Rating Curve= 0 ,0
Exp/Cntr=0.3,0.1

Type RM Length L Ch R = 1 ,5039.2  ,270.9,275.2,278
XS GIS Cut Line= 3
     1959196.924      267338.221     1959118.799      267421.554
     1959022.445      267546.554
#Sta/Elev= 26
       0  2222.3     9.5  2216.1      19 2209.71    28.6 2202.18    38.1 2194.31
    47.6 2186.56    66.6 2171.91    76.2 2164.65    85.7 2157.35    95.2 2152.04
   104.7 2149.41   114.2  2148.3   123.5 2147.34   132.8 2145.95   148.12143.335
   151.4 2142.79   160.6 2143.36   168.12144.577   179.2 2146.31   188.5 2147.39
   207.1 2149.13   216.4 2150.29   225.6 2152.58   234.9 2157.03   244.2 2162.32
     272 2178.98
#Mann= 3 , 0 , 0
       0      .1       0   148.1    .045       0   168.1      .1       0
Bank Sta=148.1,168.1
XS Rating Curve= 0 ,0
Exp/Cntr=0.3,0.1

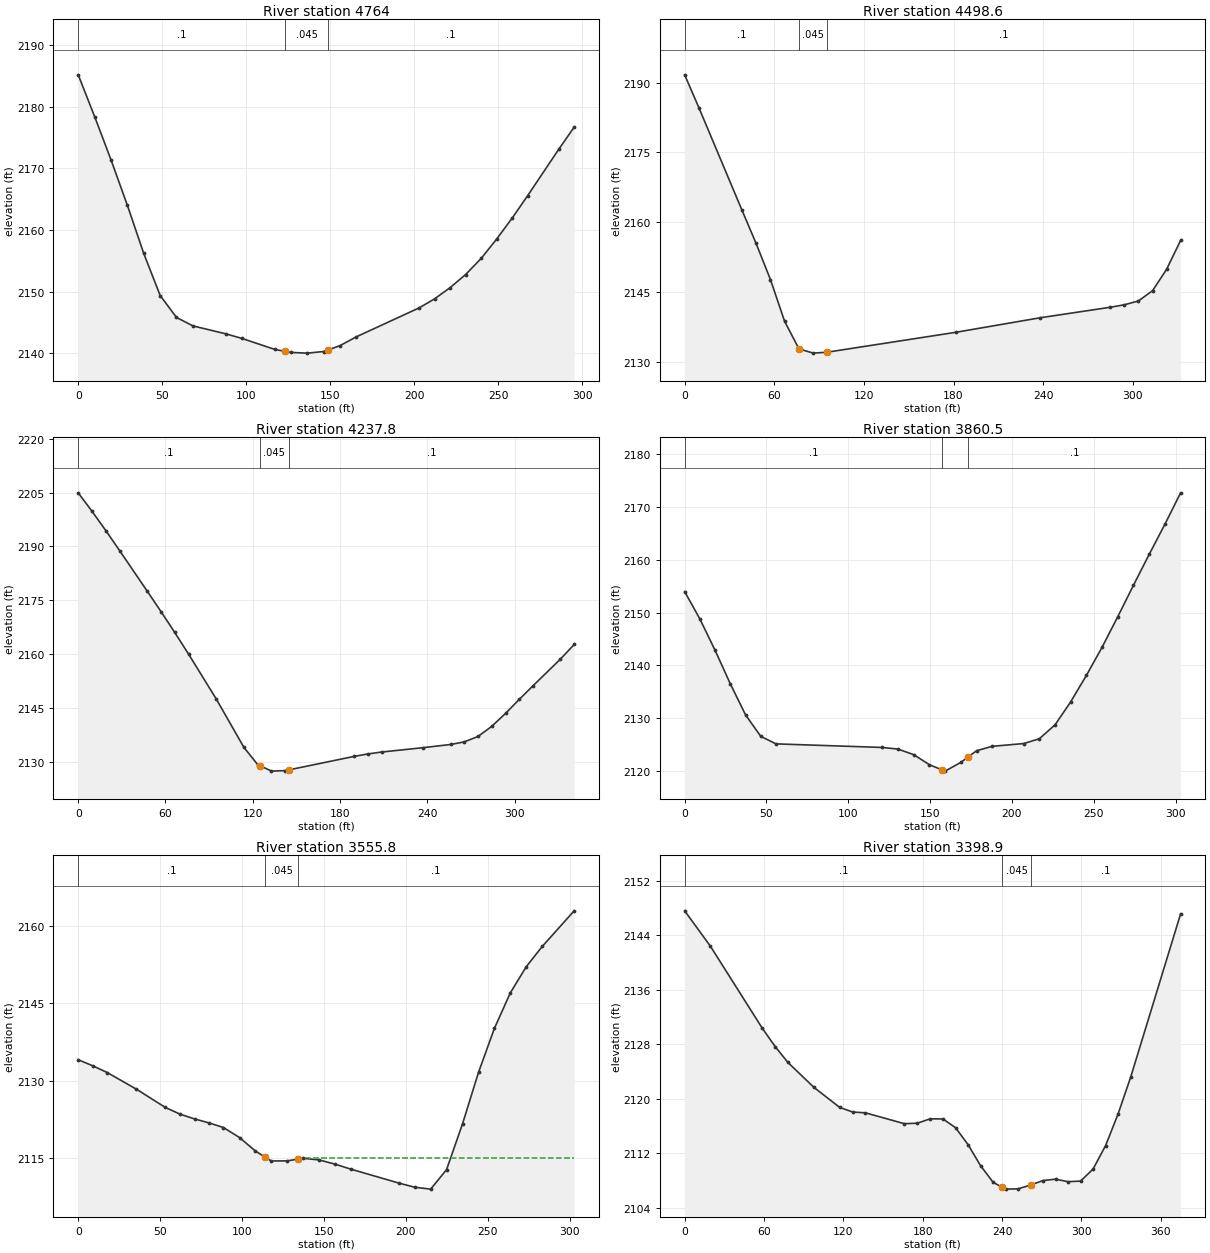
Type RM Length L Ch R = 1 ,4764    ,253.5,265.3,277.4
XS GIS Cut Line= 4
     1958985.987      267224.939     1958914.372      267275.721
      1958844.06      267327.804     1958764.633      267417.648
#Sta/Elev= 28
       0 2185.14     9.8 2178.36    19.5 2171.38    29.3 2163.97      39  2156.2
    48.8 2149.37    58.5 2145.82    68.3 2144.45    87.8 2143.17    97.5 2142.42
     117 2140.64   123.22140.327   126.7 2140.15   136.4 2140.04   146.1  2140.3
  148.582140.543   155.8 2141.25   165.6 2142.69     203 2147.38   212.2 2148.85
   221.4 2150.66   230.6 2152.78   239.9  2155.4   249.1 2158.54   258.3 2161.92
   267.5 2165.55     286 2173.06   295.2 2176.66
#Mann= 3 , 0 , 0
       0      .1       0   123.2    .045       0  148.58      .1       0
Bank Sta=123.2,148.58
XS Rating Curve= 0 ,0
Exp/Cntr=0.3,0.1

Type RM Length L Ch R = 1 ,4498.6  ,262,260.8,259.5
XS GIS Cut Line= 3
     1958885.726       267031.58     1958709.945      267077.153
     1958578.435       267150.07
#Sta/Elev= 17
       0 2191.66     9.6 2184.53    38.2  2162.7    47.8 2155.44    57.4 2147.68
    66.9 2138.69    76.5 2132.78      86 2131.86    95.22132.052   181.6 2136.34
     238 2139.46     285 2141.72   294.4 2142.25   303.8 2143.08   313.2 2145.28
   322.6 2149.86     332 2156.08
#Mann= 3 , 0 , 0
       0      .1       0    76.5    .045       0    95.2      .1       0
Bank Sta=76.5,95.2
XS Rating Curve= 0 ,0
Exp/Cntr=0.3,0.1

Type RM Length L Ch R = 1 ,4237.8  ,369.7,377.3,383.3
XS GIS Cut Line= 3
     1958854.476      266763.351     1958682.601      266818.038
     1958528.956      266864.913
#Sta/Elev= 28
       0 2204.93     9.5 2199.79      19  2194.4    28.5 2188.83    47.5 2177.52
      57 2171.82    66.4 2166.04    75.9 2160.01    94.9 2147.54   113.9 2134.07
   123.4 2129.26   124.92128.971   132.9 2127.44   142.4 2127.59   144.92127.795
   189.8 2131.55   199.3 2132.23   208.7 2132.76   237.1 2133.97     256 2134.86
   265.4 2135.57   274.9 2137.09   284.3  2139.9   293.8 2143.51   303.2 2147.39
   312.7  2151.2   331.6 2158.65     341  2162.7
#Mann= 3 , 0 , 0
       0      .1       0   124.9    .045       0   144.9      .1       0
Bank Sta=124.9,144.9
XS Rating Curve= 0 ,0
Exp/Cntr=0.3,0.1

Type RM Length L Ch R = 1 ,3860.5  ,306.2,304.6,303.2
XS GIS Cut Line= 3
     1958814.112      266478.195     1958695.622      266454.757
     1958513.331      266458.663
#Sta/Elev= 28
       0 2153.98     9.3 2148.79    18.6 2142.83    27.9 2136.49    37.2  2130.6
    46.5 2126.53    55.8  2125.1   120.8 2124.42   130.4 2124.11     140 2123.05
   149.6 2121.14   157.22120.182   159.2 2119.93   168.8  2121.6  173.362122.643
   178.4  2123.8     188 2124.64   207.2 2125.16   216.8 2126.08   226.4 2128.73
   235.9 2133.07   245.5 2138.08   255.1 2143.43   264.7 2149.23   274.3  2155.2
   283.9 2161.05   293.5 2166.76   303.1 2172.72
#Mann= 3 , 0 , 0
       0      .1       0   157.2    .045       0  173.36      .1       0
Bank Sta=157.2,173.36
XS Rating Curve= 0 ,0
Exp/Cntr=0.3,0.1

Type RM Length L Ch R = 1 ,3555.8  ,155.8,156.9,158
XS GIS Cut Line= 3
     1958842.758      266205.408     1958760.726      266171.554
     1958547.185      266185.877
#Sta/Elev= 30
       0 2134.06     8.9 2132.88    17.8 2131.56    35.5 2128.36    53.2 2124.81
    62.1 2123.52      71 2122.59    79.9 2121.81    88.7 2120.92    98.5 2118.97
   108.2 2116.36   114.32115.147   117.9 2114.43   127.7 2114.46   134.32114.795
   137.4 2114.95   147.1 2114.64   156.8 2113.82   166.6 2112.84   195.8 2110.15
   205.5 2109.34   215.2 2108.98   224.9 2112.76   234.7 2121.69   244.4 2131.61
   254.1 2140.13   263.8    2147   273.6 2152.11   283.3 2156.01   302.8 2162.92
#Mann= 3 , 0 , 0
       0      .1       0   114.3    .045       0   134.3      .1       0
#XS Ineff= 2 , 0
                          138.17         2114.98
Permanent Ineff=
       F       F
Bank Sta=114.3,134.3
XS Rating Curve= 0 ,0
Exp/Cntr=0.3,0.1

Type RM Length L Ch R = 1 ,3398.9  ,324.9,325.8,326.6
XS GIS Cut Line= 3
     1958919.581      266037.439     1958724.268      266034.835
     1958544.581      266034.835
#Sta/Elev= 30
       0 2147.57    19.5 2142.36    58.6 2130.36    68.4 2127.65    78.1 2125.31
    97.7 2121.66   117.2 2118.72     127 2118.04   136.7 2117.92     166 2116.33
   175.8 2116.39   185.6 2117.04   195.3 2117.02   204.8 2115.74   214.2 2113.27
   223.7 2110.17   233.2 2107.73   240.32106.967   242.6 2106.72   252.1 2106.76
   261.5 2107.32     271 2107.98   280.4 2108.18   289.9 2107.81   299.4  2107.9
   308.8 2109.67   318.3 2113.12   327.7 2117.75   337.2 2123.13     375 2147.13
#Mann= 3 , 0 , 0
       0      .1       0   240.3    .045       0   261.5      .1       0
Bank Sta=240.3,261.5
XS Rating Curve= 0 ,0
Exp/Cntr=0.3,0.1

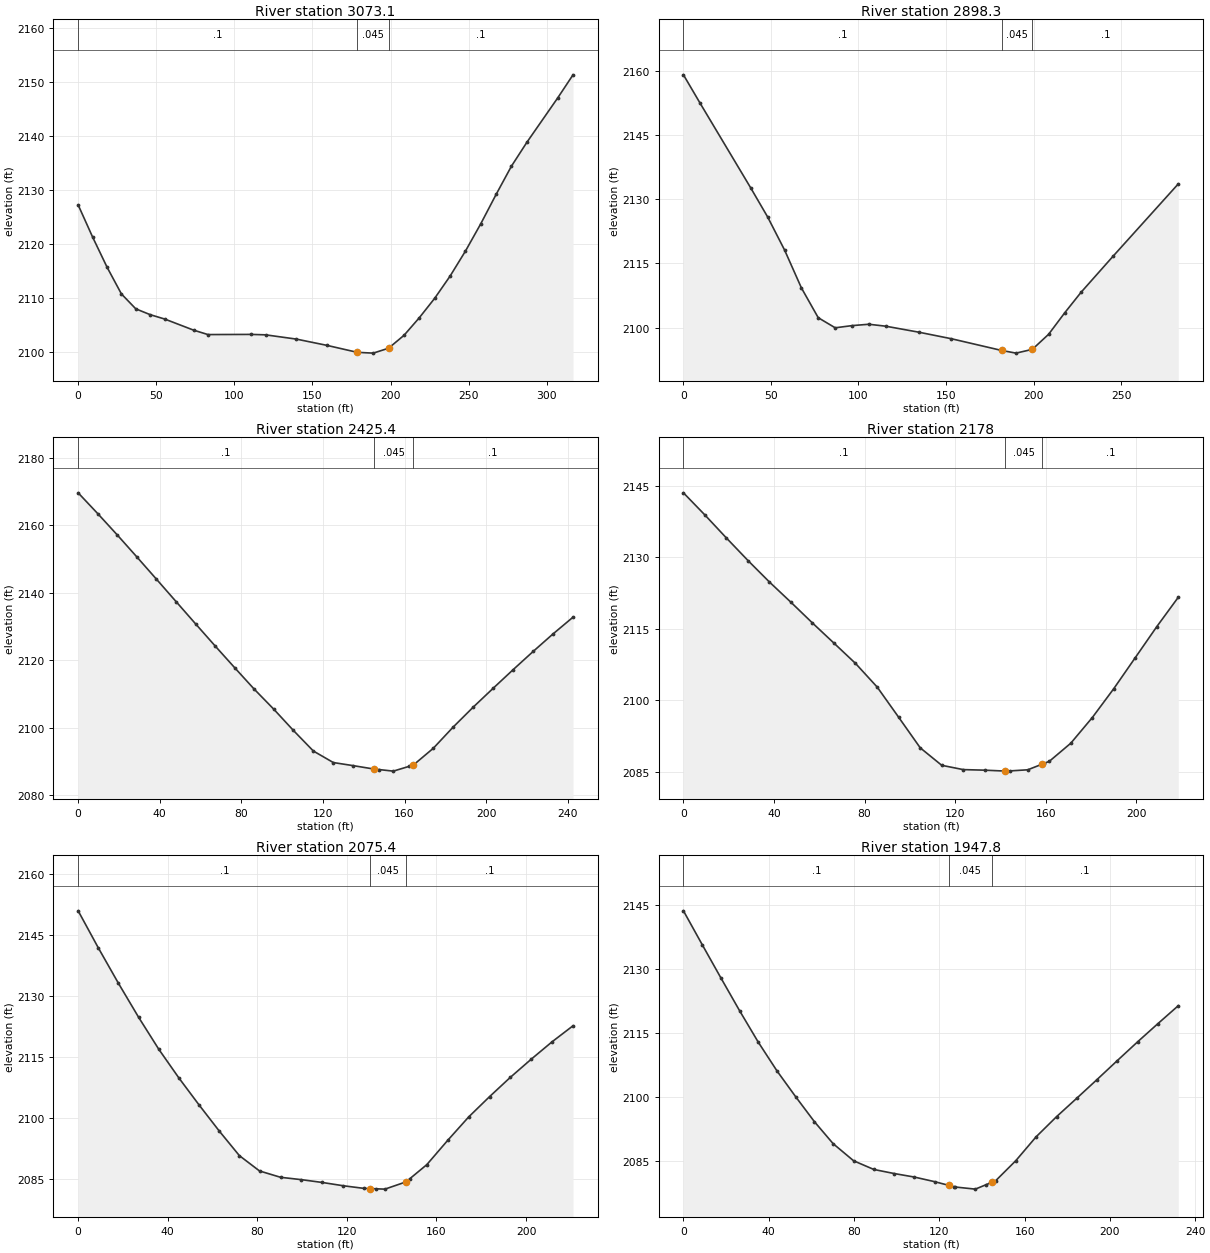
Type RM Length L Ch R = 1 ,3073.1  ,175.6,174.8,173.8
XS GIS Cut Line= 3
     1958854.476      265773.768     1958749.008      265716.476
     1958552.393      265708.663
#Sta/Elev= 27
       0 2127.21     9.2 2121.29    18.5 2115.67    27.7 2110.71    36.9 2107.95
    46.2 2106.86    55.4 2106.06    73.9    2104    83.1 2103.18   110.8 2103.21
     120 2103.13   139.7 2102.34   159.4 2101.17   178.72099.885   188.9 2099.74
   198.7 2100.65   208.6 2103.04   218.4  2106.3   228.2 2109.89   238.1 2114.02
   247.9 2118.64   257.8 2123.75   267.6 2129.18   277.4 2134.41   287.3 2138.84
     307 2147.05   316.8 2151.33
#Mann= 3 , 0 , 0
       0      .1       0   178.7    .045       0   198.7      .1       0
Bank Sta=178.7,198.7
XS Rating Curve= 0 ,0
Exp/Cntr=0.3,0.1

Type RM Length L Ch R = 1 ,2898.3  ,481.6,472.9,463.6
XS GIS Cut Line= 3
     1958872.706      265545.903     1958747.706      265539.393
     1958590.154      265539.393
#Sta/Elev= 21
       0  2159.1     9.6 2152.41    38.5 2132.62    48.1 2125.87    57.8 2118.12
    67.4 2109.28      77 2102.32    86.7 2099.96    96.3 2100.47   105.9 2100.79
   115.5 2100.34   134.4 2098.94     153 2097.41   181.82094.663     190 2094.04
   199.3 2094.92   208.6 2098.44   217.8 2103.46   227.1 2108.24   245.6 2116.77
   282.7 2133.61
#Mann= 3 , 0 , 0
       0      .1       0   181.8    .045       0   199.3      .1       0
Bank Sta=181.8,199.3
XS Rating Curve= 0 ,0
Exp/Cntr=0.3,0.1

Type RM Length L Ch R = 1 ,2425.4  ,251.5,247.4,243.5
XS GIS Cut Line= 3
     1958767.237      265025.721     1958665.674      265054.367
     1958539.372      265107.752
#Sta/Elev= 29
       0 2169.63     9.6 2163.47    19.2 2157.13    28.8 2150.62    38.4 2144.03
      48  2137.4    57.6 2130.78    67.2 2124.22    76.8 2117.76    86.3 2111.46
    95.9 2105.51   105.5 2099.23   115.3 2093.12   125.1  2089.7   134.9 2088.78
   144.7 2087.81   144.92087.797   147.4 2087.63   154.5 2087.16   162.4  2088.6
   164.3 2088.95   174.1 2093.93   183.9 2100.25   193.7 2106.14   203.5 2111.74
   213.3 2117.26   223.1 2122.65   232.8 2127.82   242.6 2132.78
#Mann= 3 , 0 , 0
       0      .1       0   144.9    .045       0   164.3      .1       0
Bank Sta=144.9,164.3
XS Rating Curve= 0 ,0
Exp/Cntr=0.3,0.1

Type RM Length L Ch R = 1 ,2178    ,113.1,102.5,91.9
XS GIS Cut Line= 3
     1958670.883      264791.346     1958578.435      264813.481
     1958474.268      264879.887
#Sta/Elev= 28
       0 2143.53     9.5 2138.87      19 2134.04    28.5 2129.32      38  2124.8
    47.5 2120.55      57  2116.2    66.5 2111.97      76 2107.72    85.6 2102.74
    95.1 2096.39   104.6 2089.99   114.1 2086.32   123.6 2085.42   133.1  2085.3
   141.92085.115   142.6  2085.1   144.4 2085.15   152.1 2085.38   158.62086.591
   159.4 2086.74   161.6 2087.15   171.1 2090.96   180.6 2096.34   190.1 2102.42
   199.6 2108.93   209.1 2115.44   218.6 2121.61
#Mann= 3 , 0 , 0
       0      .1       0   141.9    .045       0   158.6      .1       0
Bank Sta=141.9,158.6
XS Rating Curve= 0 ,0
Exp/Cntr=0.3,0.1

Type RM Length L Ch R = 1 ,2075.4  ,142.8,127.6,112.4
XS GIS Cut Line= 3
     1958551.091      264663.742     1958493.799      264721.033
     1958423.487      264842.127
#Sta/Elev= 28
       0 2150.93       9 2141.82      18 2133.09      27 2124.74      36 2116.88
      45  2109.8      54 2103.17      63 2096.76      72  2090.7      81 2086.93
    90.4 2085.37    99.7 2084.79     109  2084.1   118.4 2083.29   127.7 2082.64
   130.52082.587     133 2082.54     137 2082.46   146.4 2084.24     148 2084.97
   155.7 2088.48     165 2094.44   174.4 2100.22   183.7  2105.2     193 2109.96
   202.4 2114.46   211.7 2118.73     221 2122.65
#Mann= 3 , 0 , 0
       0      .1       0   130.5    .045       0   146.4      .1       0
Bank Sta=130.5,146.4
XS Rating Curve= 0 ,0
Exp/Cntr=0.3,0.1

Type RM Length L Ch R = 1 ,1947.8  ,236.9,231.7,226
XS GIS Cut Line= 3
     1958320.622      264611.658     1958333.643      264680.669
     1958357.081      264840.825
#Sta/Elev= 30
       0 2143.75     8.8 2135.82    17.6 2127.99    26.3 2120.36    35.1 2112.95
    43.9  2106.2    52.7 2100.12    61.4 2094.33    70.2 2089.16    79.8 2085.15
    89.3 2083.11    98.8 2082.16   108.3 2081.33   117.8 2080.25   124.62079.365
   127.1 2079.04   127.4    2079   136.9  2078.5   142.1 2079.57   144.62080.082
   146.4 2080.45   155.9 2085.18   165.4 2090.76     175 2095.49   184.5 2099.82
     194  2104.2   203.5 2108.64     213 2113.03   222.6 2117.33   232.1 2121.51
#Mann= 3 , 0 , 0
       0      .1       0   124.6    .045       0   144.6      .1       0
Bank Sta=124.6,144.6
XS Rating Curve= 0 ,0
Exp/Cntr=0.3,0.1