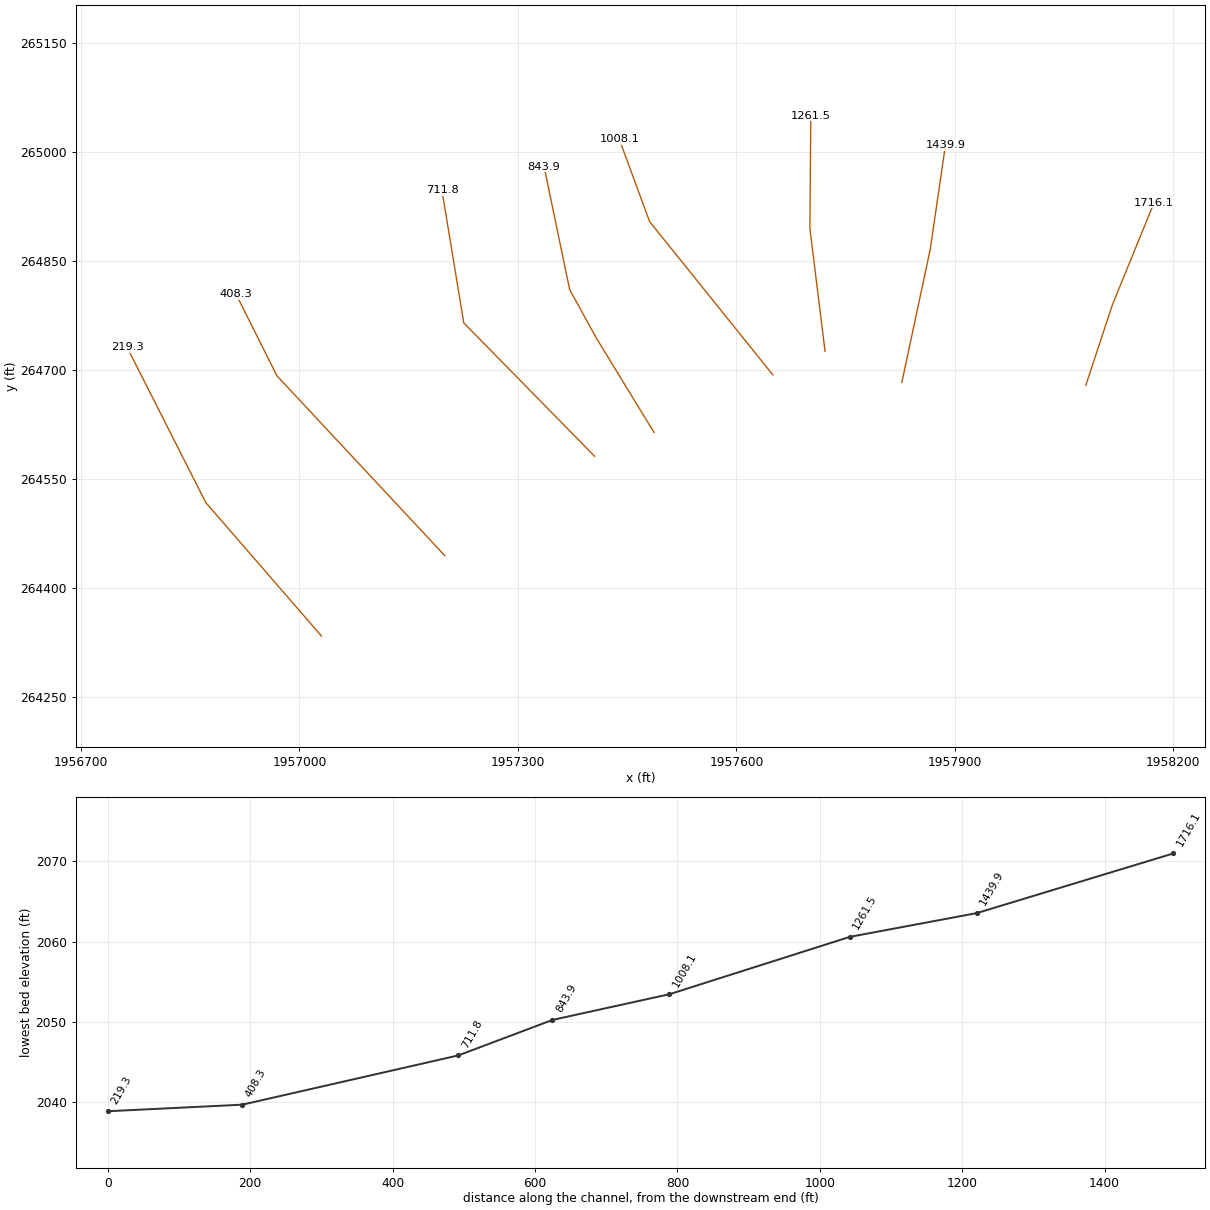
HEC-RAS study WOLFRN1.prj: WOLFRN1

--- WOLFRN1.g01 (geometry) --- (continued)

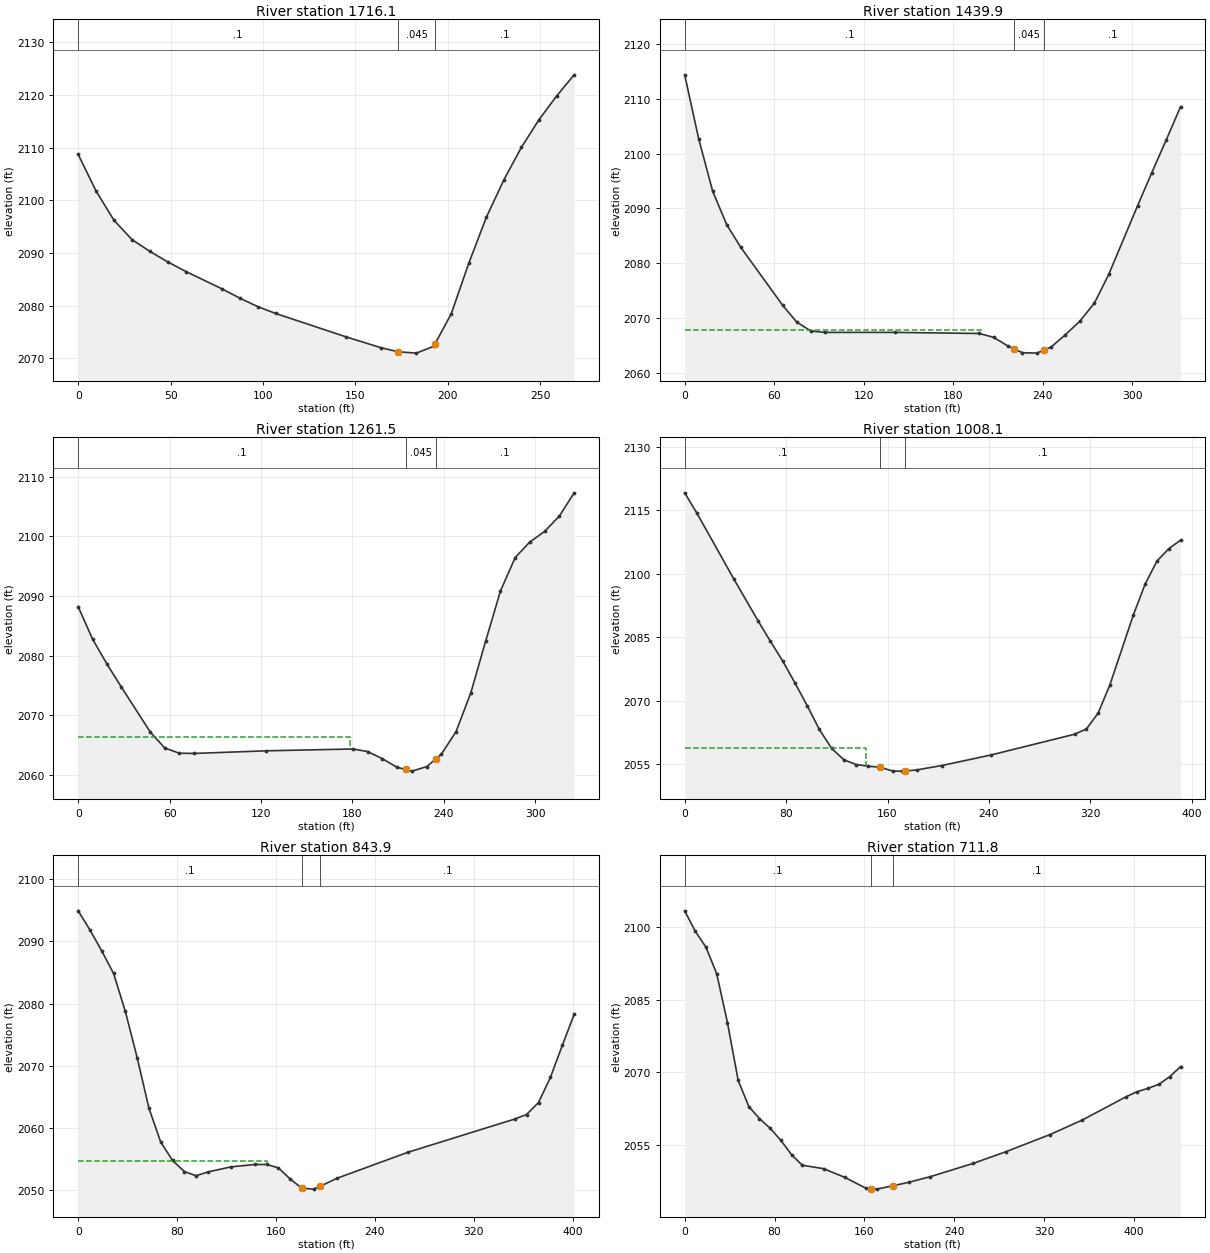
Type RM Length L Ch R = 1 ,1716.1  ,270.6,276.2,281.5
XS GIS Cut Line= 3
     1958079.737      264679.367     1958116.195      264790.044
     1958173.487      264930.669
#Sta/Elev= 25
       0 2108.69     9.7 2101.73    19.4 2096.19    29.1 2092.55    38.8  2090.3
    48.6 2088.29    58.3 2086.49    77.7 2083.22    87.4 2081.45    97.1 2079.84
   106.8 2078.54     145 2074.09     164 2072.02   173.22071.265     183 2071.01
   192.4 2072.31   193.2 2072.83   201.9 2078.48   211.4 2088.08   220.9  2096.8
   230.4  2103.9   239.9 2110.07   249.4  2115.3   258.9 2119.78   268.4  2123.8
#Mann= 3 , 0 , 0
       0      .1       0   173.2    .045       0   193.2      .1       0
Bank Sta=173.2,193.2
XS Rating Curve= 0 ,0
Exp/Cntr=0.3,0.1

Type RM Length L Ch R = 1 ,1439.9  ,174.6,178.4,182
XS GIS Cut Line= 3
     1957827.133      264683.273     1957866.195      264866.867
     1957887.029      265010.096
#Sta/Elev= 26
       0 2114.41     9.4  2102.7    18.8 2093.11    28.2 2087.02    37.5 2082.92
    65.7 2072.28    75.1 2069.23    84.5  2067.6    93.8 2067.34   140.8 2067.34
   197.4 2067.14     207 2066.45   216.6 2064.86   220.82064.327   226.3 2063.63
     236 2063.55   240.82064.108   245.6 2064.66   255.2 2066.92   264.9  2069.4
   274.6 2072.68   284.2 2077.92   303.5 2090.45   313.1 2096.54   322.8 2102.54
   332.4 2108.61
#Mann= 3 , 0 , 0
       0      .1       0   220.8    .045       0   240.8      .1       0
#XS Ineff= 2 , 0
          198.37 2067.75
Permanent Ineff=
       F       F
Bank Sta=220.8,240.8
XS Rating Curve= 0 ,0
Exp/Cntr=0.3,0.1

Type RM Length L Ch R = 1 ,1261.5  ,238,253.4,269.2
XS GIS Cut Line= 3
     1957721.664      264726.242     1957700.831      264895.512
     1957702.133       265050.46
#Sta/Elev= 27
       0 2088.19     9.5 2082.72      19 2078.51    28.4 2074.67    47.4 2067.11
    56.8 2064.47    66.3 2063.59    75.8 2063.55   123.2 2063.99   180.2  2064.3
   189.9 2063.87   199.6 2062.67   209.3 2061.22   214.92060.854     219 2060.58
   228.7 2061.33   234.92062.668   238.3  2063.4     248 2067.23   257.7 2073.75
   267.4 2082.41   277.1 2090.82   286.8 2096.46   296.4 2099.07   306.1 2100.84
   315.8 2103.43   325.5 2107.33
#Mann= 3 , 0 , 0
       0      .1       0   214.9    .045       0   234.9      .1       0
#XS Ineff= 2 , 0
          178.36 2066.28
Permanent Ineff=
       F       F
Bank Sta=214.9,234.9
XS Rating Curve= 0 ,0
Exp/Cntr=0.3,0.1

Type RM Length L Ch R = 1 ,1008.1  ,168.3,164.2,160
XS GIS Cut Line= 3
     1957650.049      264693.689     1957480.779      264904.627
     1957439.112      265017.908
#Sta/Elev= 29
       0 2119.09     9.7 2114.26    38.6 2098.84      58 2088.83    67.6 2084.07
    77.3 2079.41    86.9 2074.28    96.6 2068.89   106.2 2063.26   115.9 2058.78
   125.6 2056.08   135.2 2054.97   144.9 2054.57     1542054.335   164.2 2053.42
   171.5 2053.41     1742053.413   183.5 2053.72   202.8 2054.73   241.5 2057.21
   307.6 2062.12   316.9 2063.37   326.2 2067.13   335.4 2073.77     354 2090.34
   363.3 2097.62   372.6    2103   381.9 2105.92   391.2 2107.92
#Mann= 3 , 0 , 0
       0      .1       0     154    .045       0     174      .1       0
#XS Ineff= 2 , 0
          143.11  2058.8
Permanent Ineff=
       F       F
Bank Sta=154,174
XS Rating Curve= 0 ,0
Exp/Cntr=0.3,0.1

Type RM Length L Ch R = 1 ,843.9   ,125.4,132.1,137.8
XS GIS Cut Line= 4
     1957486.873      264614.501     1957407.446      264744.709
     1957370.988      264811.116     1957335.831      264980.386
#Sta/Elev= 28
       0 2094.92     9.5 2091.84    19.1 2088.46    28.6 2084.85    38.1 2078.78
    47.7 2071.32    57.2 2063.22    66.7 2057.78    76.3 2054.81    85.8 2053.03
    95.3 2052.35   104.9 2052.96   123.9 2053.79     143 2054.16   152.5 2054.16
     162 2053.61   171.5 2051.82   180.9 2050.35   190.4  2050.2   195.9 2050.67
   209.3 2051.94   266.7 2056.12   353.1 2061.46   362.7 2062.19   372.4 2064.12
     382 2068.16   391.6 2073.29   401.2 2078.28
#Mann= 3 , 0 , 0
       0      .1       0   180.9    .045       0   195.9      .1       0
#XS Ineff= 2 , 0
          152.71 2054.78
Permanent Ineff=
       F       F
Bank Sta=180.9,195.9
XS Rating Curve= 0 ,0
Exp/Cntr=0.3,0.1

Type RM Length L Ch R = 1 ,711.8   ,303.9,303.5,303.5
XS GIS Cut Line= 3
     1957405.258       264581.71      1957225.57      264765.304
     1957195.622      264947.596
#Sta/Elev= 30
       0 2103.44     9.5 2099.18      19 2095.88    28.5 2090.41    38.1 2080.26
    47.6 2068.34    57.1 2062.89    66.6 2060.38    76.1 2058.39    85.6 2055.89
    95.2  2052.9   104.7 2050.72   123.7 2050.01   142.7 2048.19   161.8 2045.91
   165.82045.849   171.3 2045.77   185.82046.486   199.8  2047.2   218.8 2048.36
   256.9  2051.1   286.1 2053.53     325 2057.05   354.1 2060.09     393 2064.91
   402.7 2065.94   412.5 2066.65   422.2 2067.49   431.9 2069.07   441.6 2071.17
#Mann= 3 , 0 , 0
       0      .1       0   165.8    .045       0   185.8      .1       0
Bank Sta=165.8,185.8
XS Rating Curve= 0 ,0
Exp/Cntr=0.3,0.1

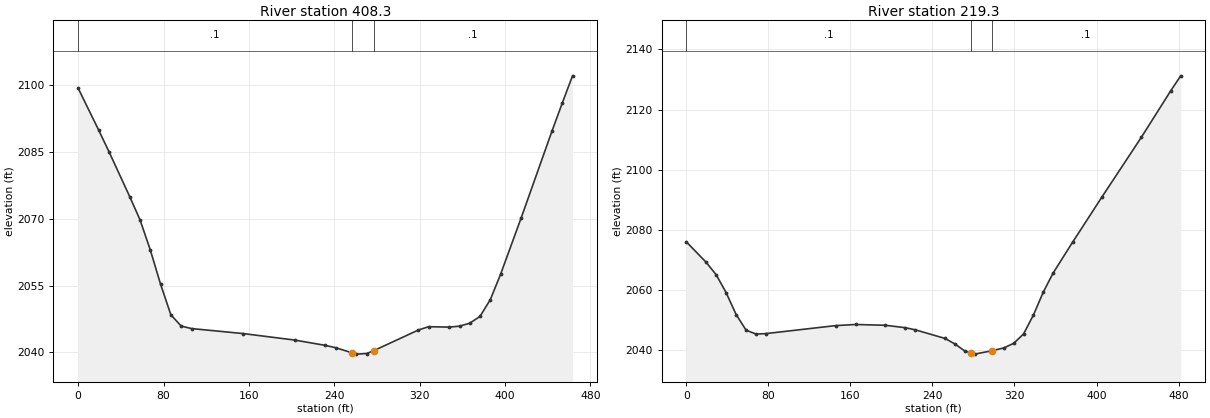
Type RM Length L Ch R = 1 ,408.3   ,195.6,189,181.8
XS GIS Cut Line= 3
     1957199.529      264444.992      1956969.06      264692.387
      1956913.07      264804.367
#Sta/Elev= 30
       0 2099.35    19.3  2089.9      29 2085.03    48.3 2075.01      58 2069.77
    67.6 2063.03    77.3 2055.28    86.9 2048.44    96.6 2045.91   106.3 2045.35
   154.6 2044.23   202.9 2042.77   231.8 2041.57   241.5 2041.04   256.92039.896
   260.8 2039.61   270.5 2039.75   276.92040.376   318.8 2045.02   328.4 2045.77
   347.7 2045.68   357.4 2045.89     367 2046.56   376.6 2048.08   386.3 2051.87
   395.9 2057.56   415.2 2070.22     444 2089.67   453.7 2096.01   463.3 2102.12
#Mann= 3 , 0 , 0
       0      .1       0   256.9    .045       0   276.9      .1       0
Bank Sta=256.9,276.9
XS Rating Curve= 0 ,0
Exp/Cntr=0.3,0.1

Type RM Length L Ch R = 1 ,219.3   ,222.7,219.3,215.9
XS GIS Cut Line= 3
     1957030.258      264334.314     1956871.404      264517.908
     1956763.331       264731.45
#Sta/Elev= 30
       0 2076.09    19.4 2069.26    29.1 2065.16    38.8 2059.23    48.6 2051.93
    58.3 2046.75      68 2045.45    77.7 2045.61   145.7 2048.26   165.1 2048.63
   194.2 2048.37   213.6 2047.56   223.4 2046.85   252.4 2043.99   261.9 2042.16
   271.5 2039.84   277.72039.163   281.1 2038.79   297.72039.895   309.8 2040.86
   319.4 2042.42   328.9 2045.51   338.5 2051.78   348.1 2059.38   357.7 2065.72
   376.8 2076.01   405.5 2091.07   443.8 2110.82   472.5 2126.29   482.1 2131.19
#Mann= 3 , 0 , 0
       0      .1       0   277.7    .045       0   297.7      .1       0
Bank Sta=277.7,297.7
XS Rating Curve= 0 ,0
Exp/Cntr=0.3,0.1

Chan Stop Cuts=-1
Use User Specified Reach Order=0
Composite Channel Slope=5